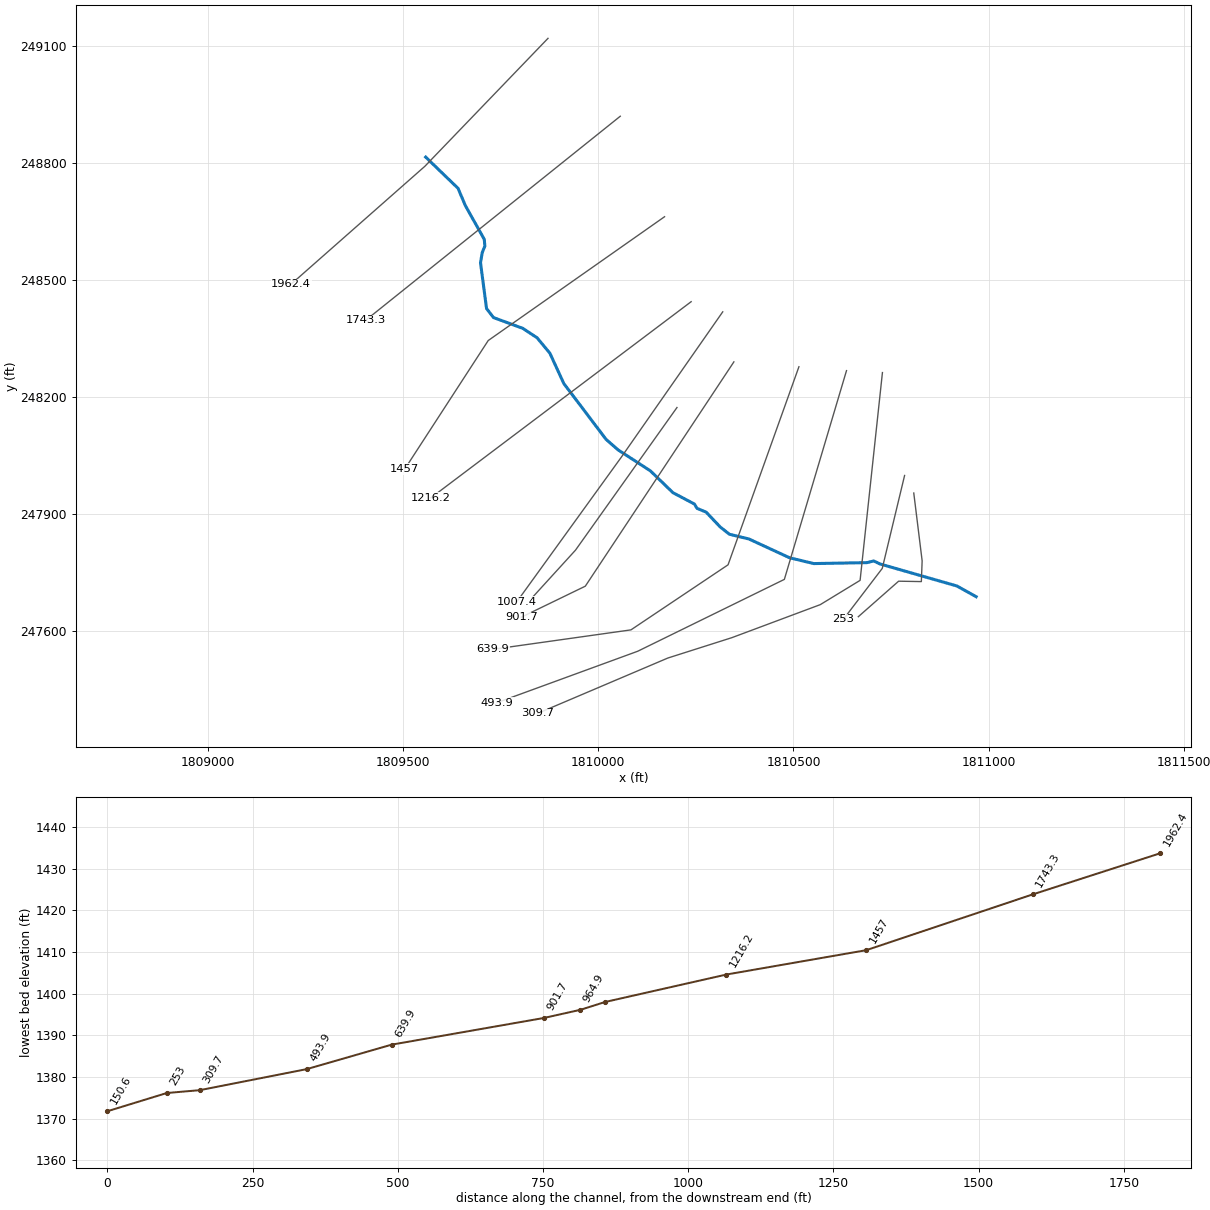
--- HurrcaneBr.prj (project) ---

Proj Title=HurrcaneBr
Current Plan=p01
Default Exp/Contr=0,0
English Units
Geom File=g01
Flow File=f01
Plan File=p01
BEGIN DESCRIPTION:
END DESCRIPTION:
DSS Export Rating Curves= 0
DSS Export Rating Curve Sorted= 0
DSS Export Volume Flow Curves= 0
DXF OffsetX= 0
DXF OffsetY= 0
DXF ScaleX= 0
DXF ScaleY= 0

--- HurrcaneBr.p01 (plan) ---

Plan Title=Floodplain
Program Version=4.00
Geom File=g01
Flow File=f01
K Sum by GR=0
Std Step Tol=0.01
Critical Tol=0.01
Num of Std Step Trials=20
Max Error Tol=0.3
Flow Tol Ratio=0.001
Split Flow NTrial=30
Split Flow Tol=0.02
Split Flow Ratio=0.02
Log Output Level=0
Friction Slope Method=1
Unsteady Friction Slope Method=2
Unsteady Bridges Friction Slope Method=1
Global Log Level=0
CheckData=False
Run HTab=0
Run UNet=0
Run PostProcess=0
UNET Theta=0
UNET Theta Warmup=0
UNET ZTol=0
UNET ZSATol=0
UNET MxIter=0
UNET MaxInSteps=0
UNET DtIC=0
UNET DtMin=0
UNET MaxCRTS=0
UNET WFStab=0
UNET SFStab=0
UNET WFX=0
UNET SFX=0
UNET DSS MLevel=0
UNET DZMax Abort=0
UNET Convert EG Bridges=0
UNET Use Existing IB Tables=0
UNET Froude Limit=0
UNET Froude Power=0
Write IC File=0
Echo Input=False
Echo Output=False
Write Detailed=0

--- HurrcaneBr.f01 (steady flow) ---

Flow Title=NFF Regression Equation
Program Version=4.00
Number of Profiles=1
Profile Names=P100yr
River Rch & RM=HurrcaneBr,Main      ,1962.4
556.9640
River Rch & RM=HurrcaneBr,Main      ,309.7
584.4899
Boundary for River Rch & Prof#=HurrcaneBr,Main      ,1
Up Type=0
Dn Type=3
Dn Slope=0.038491

--- HurrcaneBr.g01 (geometry) ---

Geom Title=USGS 10m DEM
Program Version=4.00

River Reach=HurrcaneBr      ,Main
Reach XY= 30
     1809558.278      248814.261     1809641.105      248734.357
     1809659.619      248690.508     1809708.255      248603.713
     1809709.704      248586.336     1809702.946      248569.441
     1809698.601      248543.857     1809714.048      248426.558
     1809731.908      248403.388     1809806.729      248375.873
     1809843.415      248351.738     1809876.239      248312.155
      1809911.96      248234.439     1810020.088      248091.556
     1810050.981      248064.524     1810133.525      248010.943
      1810191.45      247954.948     1810246.451      247925.857
     1810253.053      247914.855     1810276.439       247905.11
     1810312.493      247867.107      1810335.88      247848.593
     1810386.293      247836.297     1810489.766      247788.413
     1810552.036      247773.448     1810688.161      247775.862
     1810705.539      247780.207     1810721.468      247772.483
     1810918.851      247715.976     1810967.811      247688.622

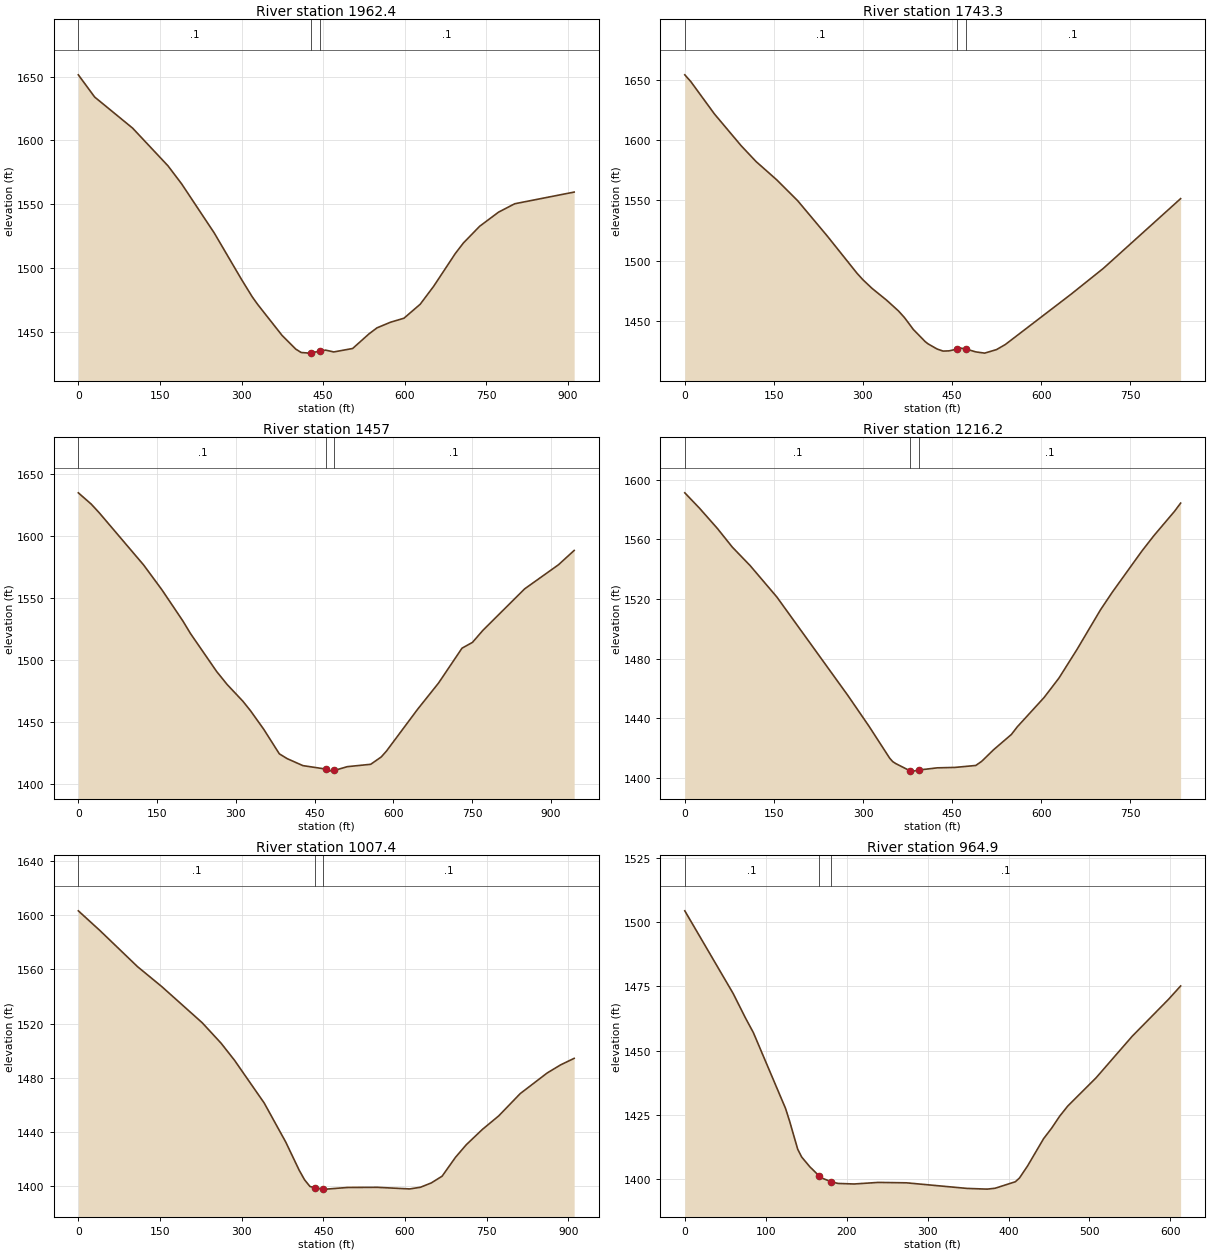
Type RM Length L Ch R = 1 ,1962.4  ,222,219.1,216.4
XS GIS Cut Line= 3
     1809871.426      249118.451     1809556.166       248790.83
     1809213.395      248488.766
#Sta/Elev= 30
       0 1651.32      30 1633.95    99.9 1609.58   164.9 1580.09   189.9 1566.03
   249.8 1527.66   299.8 1491.41   319.8  1477.6   329.8 1471.66   374.7 1447.39
   399.7 1436.77   409.7 1434.11   424.7 1433.62   428.6  1433.8   443.6 1435.21
   454.7 1435.97   469.6 1434.54   504.3 1437.25   534.1 1448.58     549 1453.38
   573.8 1457.78   598.7 1460.94   628.5 1471.88   653.3 1485.95     693 1511.53
   707.9 1519.78   737.7 1532.82   772.5  1543.9   802.3 1550.47   911.5  1559.6
#Mann= 3 , 0 , 0
       0      .1       0   428.6    .045       0   443.6      .1       0
Bank Sta=428.6,443.6
XS Rating Curve= 0 ,0
Exp/Cntr=0.3,0.1

Type RM Length L Ch R = 1 ,1743.3  ,289.7,286.3,283.2
XS GIS Cut Line= 2
     1810056.501      248918.976     1809405.073      248396.839
#Sta/Elev= 30
       0  1653.9      10 1648.38      50 1621.49      95 1595.22     120  1582.2
     155 1566.98     190 1549.84     240 1520.56     290 1489.81     300 1484.42
     315 1477.45   339.9 1467.53   359.9 1458.61   369.9 1453.17   384.9  1443.3
   404.9 1433.26   409.9 1431.36   424.9 1427.15   434.9 1425.47   444.9 1425.65
   457.8 1427.03   464.9 1427.89   472.8 1427.26   489.9 1424.82   504.9 1423.78
   524.9  1426.7   539.9 1430.96   649.9  1472.3   704.9 1493.91   834.9 1551.52
#Mann= 3 , 0 , 0
       0      .1       0   457.8    .045       0   472.8      .1       0
Bank Sta=457.8,472.8
XS Rating Curve= 0 ,0
Exp/Cntr=0.3,0.1

Type RM Length L Ch R = 1 ,1457    ,238,240.8,243.4
XS GIS Cut Line= 3
     1810169.913       248661.66     1809718.355      248344.625
      1809504.71      248015.596
#Sta/Elev= 30
       0 1634.99    24.8 1625.79    39.8 1618.89   124.3 1576.78   159.1 1556.77
   198.8 1531.76   213.7 1521.34   263.4 1490.79   283.3 1480.33   313.2 1466.87
   328.1 1458.98   352.9 1444.26   382.7 1424.37   397.6  1420.5   427.5 1414.87
   472.2 1412.01   482.2 1410.42   487.2 1410.93     512 1414.01   556.7 1415.94
   576.6 1421.83   586.5 1426.51   646.1 1460.42   685.8 1481.49   730.5 1509.64
   750.4 1514.31   770.2    1524   849.7 1557.48   914.2 1576.96     944 1588.49
#Mann= 3 , 0 , 0
       0      .1       0   472.2    .045       0   487.2      .1       0
Bank Sta=472.2,487.2
XS Rating Curve= 0 ,0
Exp/Cntr=0.3,0.1

Type RM Length L Ch R = 1 ,1216.2  ,201.6,208.8,215.7
XS GIS Cut Line= 2
     1810238.006       248444.08     1809571.659      247941.834
#Sta/Elev= 30
       0 1591.29      25 1580.87      55 1567.32      80 1554.85   109.9 1542.49
   154.9 1521.41   274.8 1455.13   309.8 1434.82   344.8 1413.26   349.8 1411.01
   354.8 1409.69     379 1404.79   384.7 1404.58     394 1405.33   424.7 1406.78
   454.7 1407.07   489.7 1408.38   499.7 1411.18   519.6 1418.91   549.6 1429.18
   559.6 1434.33   604.6 1453.95   629.6 1466.98   659.6 1485.94   699.5 1512.77
   719.5 1524.67   769.5 1552.38   789.5  1562.6   824.4 1579.02   834.4 1584.39
#Mann= 3 , 0 , 0
       0      .1       0     379    .045       0     394      .1       0
Bank Sta=379,394
XS Rating Curve= 0 ,0
Exp/Cntr=0.3,0.1

Type RM Length L Ch R = 1 ,1007.4  ,42.8,42.6,42.5
XS GIS Cut Line= 3
     1810318.906      248418.108     1810058.409      248044.827
     1809791.523      247675.534
#Sta/Elev= 30
       0 1603.21    39.6  1588.7   108.8 1562.02   153.4  1547.3   227.6 1520.67
   262.2 1505.62     287 1492.96   341.4 1461.52     381 1432.71   405.7 1411.95
   415.6 1404.87   425.5 1399.96   435.2 1398.87   450.2  1398.1   450.2 1398.09
   455.2    1398   494.8 1399.22   549.3 1399.32   608.7 1398.15   628.5 1399.39
   648.3 1402.56   668.2 1407.53   692.9  1421.5   712.7 1430.76   742.4 1442.09
   772.2    1452   811.8 1468.46   861.3 1483.66   886.1 1489.66   910.8 1494.43
#Mann= 3 , 0 , 0
       0      .1       0   435.2    .045       0   450.2      .1       0
Bank Sta=435.2,450.2
XS Rating Curve= 0 ,0
Exp/Cntr=0.3,0.1

Type RM Length L Ch R = 1 ,964.9   ,62.4,63.1,63.9
XS GIS Cut Line= 3
     1810201.698      248173.057     1809941.827      247807.808
     1809831.091      247686.356
#Sta/Elev= 30
       0 1504.35    59.8 1472.18    74.7 1462.84    84.7    1457   124.5 1427.49
   129.5 1422.54   139.5 1411.64   144.4 1408.61   154.4 1404.84   165.8 1401.31
   169.3 1400.42   180.8 1399.02   189.3 1398.33   209.2 1398.12   239.1 1398.73
   273.9 1398.57   348.6  1396.4   373.6 1396.12   383.5 1396.47   408.4 1398.99
   413.4 1400.41   423.4 1405.08   443.3 1415.74   453.2 1419.81   463.2  1424.5
   473.2 1428.45     508 1439.36   552.8 1455.58   597.7 1469.95   612.6 1475.13
#Mann= 3 , 0 , 0
       0      .1       0   165.8    .045       0   180.8      .1       0
Bank Sta=165.8,180.8
XS Rating Curve= 0 ,0
Exp/Cntr=0.3,0.1

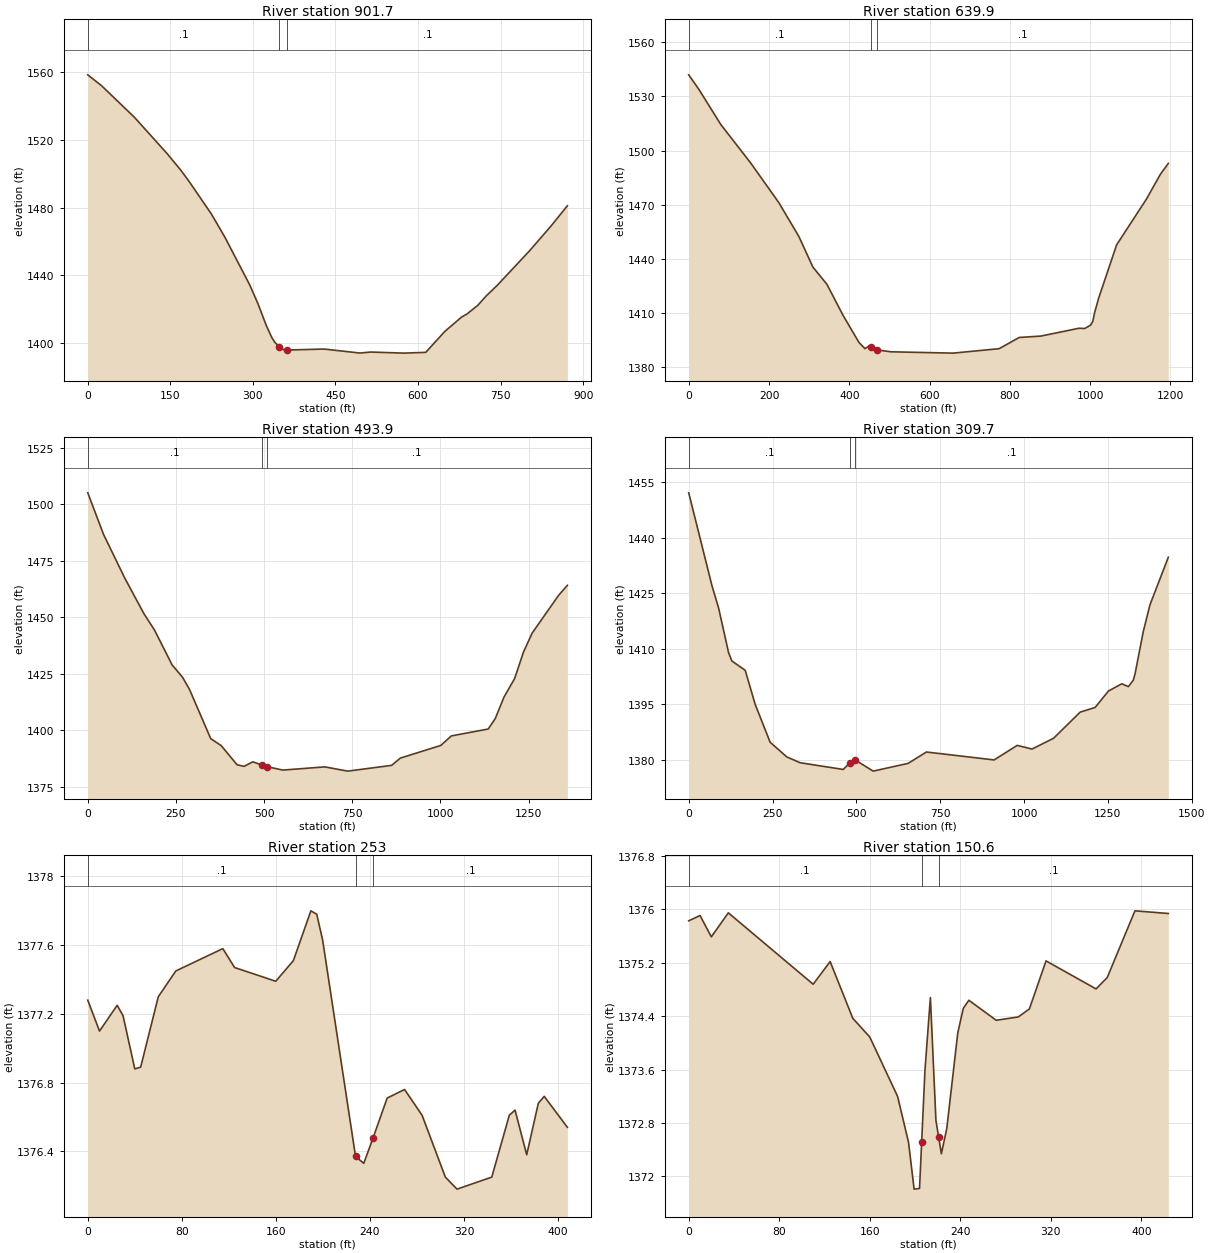
Type RM Length L Ch R = 1 ,901.7   ,256.2,261.8,267.4
XS GIS Cut Line= 3
     1810347.406      248289.925     1809966.992      247715.574
     1809802.891       247636.01
#Sta/Elev= 30
       0 1558.46      25 1552.05    84.9 1533.35   144.8 1511.71   169.7  1501.9
   184.7 1495.23   224.6 1476.29   249.6 1462.31   294.5 1434.27   309.5  1423.1
   324.5 1410.32   334.5 1403.27   339.5  1400.7   347.7  1397.9   354.4  1396.4
   362.7 1395.99   429.3 1396.57   494.2 1394.22   514.2  1394.8   574.1 1394.16
     614 1394.61     649 1407.08   678.9 1415.39   688.9 1417.25   708.6 1422.38
   723.4  1427.8   743.1 1433.91   802.3 1454.47   841.7 1469.23   871.3 1481.17
#Mann= 3 , 0 , 0
       0      .1       0   347.7    .045       0   362.7      .1       0
Bank Sta=347.7,362.7
XS Rating Curve= 0 ,0
Exp/Cntr=0.3,0.1

Type RM Length L Ch R = 1 ,639.9   ,144.7,146,147.2
XS GIS Cut Line= 4
     1810513.992      248277.493     1810332.488      247770.274
     1810083.851      247603.688     1809730.787       247553.96
#Sta/Elev= 30
       0 1541.94    24.9 1534.02    79.8 1514.46   154.6 1493.02   224.5 1471.12
   274.4 1452.38   309.3 1435.44   344.2 1425.91   384.1 1408.82     424 1393.71
     439 1390.23   448.9 1391.75   453.9 1391.19   453.9 1391.18   468.9 1389.56
   503.8  1388.5   658.4 1387.77   773.2 1390.23     823 1396.43   877.6 1397.23
   971.7 1401.54   986.6 1401.43  1001.4 1403.36  1006.4 1405.34  1011.3 1410.45
  1021.2  1418.3  1065.8 1447.74  1140.1  1473.1  1174.7  1486.8  1194.6 1492.88
#Mann= 3 , 0 , 0
       0      .1       0   453.9    .045       0   468.9      .1       0
Bank Sta=453.9,468.9
XS Rating Curve= 0 ,0
Exp/Cntr=0.3,0.1

Type RM Length L Ch R = 1 ,493.9   ,180.1,184.3,188.4
XS GIS Cut Line= 4
     1810635.824      248267.548     1810476.697      247732.979
     1810101.256      247548.987     1809740.732       247417.21
#Sta/Elev= 30
       0 1505.01    44.8 1486.59   104.6 1467.39   159.4 1451.51   189.2 1444.31
     239 1428.93   268.9 1423.39   288.8 1417.93   348.6 1396.27   378.5 1393.17
   423.3 1384.72   443.2 1384.03   468.1 1386.02   493.2 1384.64   508.2 1383.89
   552.8 1382.37   672.2 1383.79   736.9 1381.91   861.4 1384.45   886.3 1387.68
  1000.8 1393.27  1030.7 1397.48  1135.4 1400.54  1155.3 1405.17  1180.2 1414.72
  1210.2 1422.85  1235.1 1434.51    1260    1443  1334.8 1459.66  1359.7 1464.09
#Mann= 3 , 0 , 0
       0      .1       0   493.2    .045       0   508.2      .1       0
Bank Sta=493.2,508.2
XS Rating Curve= 0 ,0
Exp/Cntr=0.3,0.1

Type RM Length L Ch R = 1 ,309.7   ,60.2,56.7,47.5
XS GIS Cut Line= 6
      1810727.82      248262.575     1810670.634      247730.492
     1810568.693      247668.333     1810342.433      247583.797
     1810178.333      247531.583      1809845.16       247389.86
#Sta/Elev= 30
       0 1452.13    69.4 1426.99    89.2 1420.95   118.9 1408.89   128.8 1406.64
   168.5 1404.13   198.2 1394.92   242.8 1384.68   292.4 1380.71     332 1379.14
   460.8 1377.31     482 1379.19     497 1379.86   550.1 1376.86   654.5 1378.96
   708.8 1382.03   910.8 1379.89   979.7 1383.82    1024 1382.83  1088.1 1385.74
  1167.5 1392.82  1212.1 1394.08  1251.8 1398.52  1291.5 1400.48  1311.3 1399.72
  1326.2  1401.5  1331.2  1403.2    1356 1414.74  1375.8 1421.88  1430.4 1434.72
#Mann= 3 , 0 , 0
       0      .1       0     482    .045       0     497      .1       0
Bank Sta=482,497
XS Rating Curve= 0 ,0
Exp/Cntr=0.3,0.1

Type RM Length L Ch R = 1 ,253     ,97.9,102.4,81.3
XS GIS Cut Line= 3
     1810784.564      247999.044     1810727.357      247761.023
     1810628.267      247631.286
#Sta/Elev= 30
       0 1377.28      10  1377.1      25 1377.25      30 1377.19      40 1376.88
      45 1376.89      60  1377.3    74.9 1377.45   114.9 1377.58   124.9 1377.47
   159.9 1377.39   174.9 1377.51   189.8  1377.8   194.8 1377.78   199.8 1377.63
   227.8 1376.37   234.8 1376.33   242.8 1376.48   254.7 1376.71   269.5 1376.76
   284.4 1376.61   304.2 1376.25   314.1 1376.18   343.7 1376.25   358.6 1376.61
   363.5 1376.64   373.4 1376.38   383.3 1376.68   388.3 1376.72     408 1376.54
#Mann= 3 , 0 , 0
       0      .1       0   227.8    .045       0   242.8      .1       0
Bank Sta=227.8,242.8
XS Rating Curve= 0 ,0
Exp/Cntr=0.3,0.1

Type RM Length L Ch R = 1 ,150.6   ,161.3,150.6,171.2
XS GIS Cut Line= 5
     1810808.059      247954.096     1810829.512      247780.432
     1810827.469      247727.312     1810769.241      247728.333
     1810666.064      247637.416
#Sta/Elev= 30
       0 1375.83      10 1375.91      20 1375.59      35 1375.95     110 1374.88
     125 1375.22     145 1374.37     160 1374.09   184.6  1373.2   194.3 1372.51
   199.2 1371.81     204 1371.82   205.9 1372.52   208.8 1373.59   213.6 1374.68
   218.5 1372.84   220.9 1372.59   223.3 1372.34   228.1 1372.72   237.8 1374.15
   242.7 1374.52   247.6 1374.64   271.8 1374.34   291.3 1374.39   301.1 1374.51
   315.8 1375.23     360 1374.81   369.9 1374.98   394.4 1375.98   423.9 1375.94
#Mann= 3 , 0 , 0
       0      .1       0   205.9    .045       0   220.9      .1       0
Bank Sta=205.9,220.9
XS Rating Curve= 0 ,0
Exp/Cntr=0.3,0.1

Chan Stop Cuts=-1
Use User Specified Reach Order=0